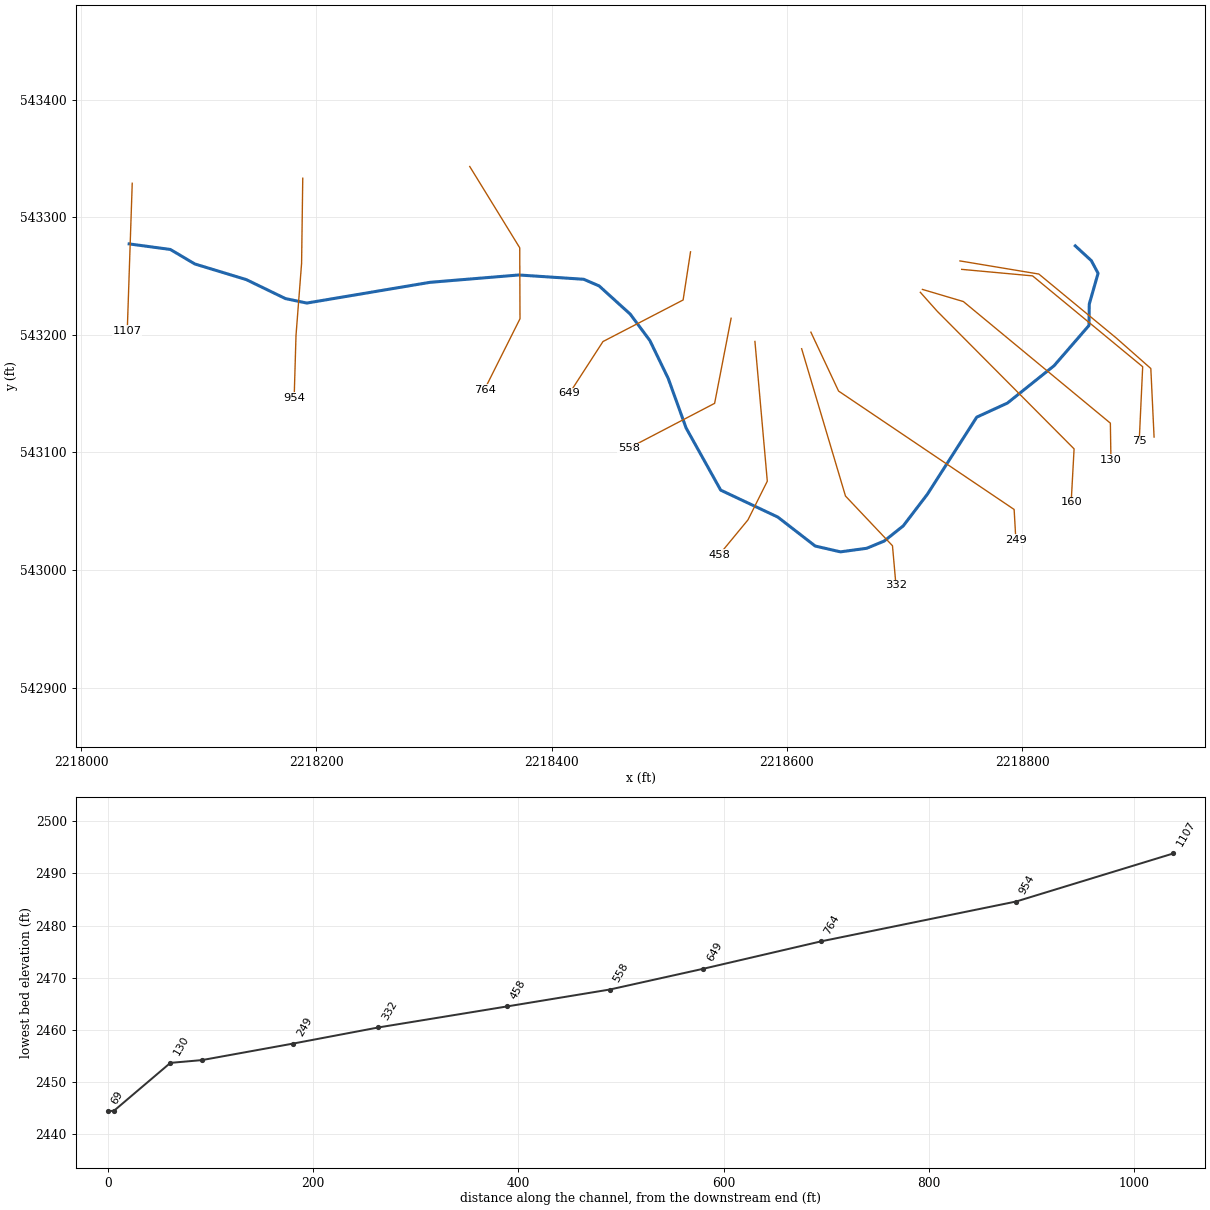
--- ELKRIVT1.prj (project) ---

Proj Title=ELKRIVT1
Current Plan=p01
Default Exp/Contr=0,0
English Units
Geom File=g01
Flow File=f01
Plan File=p01
BEGIN DESCRIPTION:
----------MODEL BY WOOD PLC 2022----------
AFH study
Randolph County, WV
HEC-RAS Version: RAS 6.2
Vertical Datum: NAVD88
Projection: NAD 1983 StatePlane West Virginia S FIPS 4702 (US Feet)
Terrain: 1-meter LIDAR (FEMA Region III 3DEP collected 2016-2018)
Land Use: 2019 NLCD
Hydrologic Method:
WV SIR2010-5033 regression equations
Additional Model Notes:
None
END DESCRIPTION:
DSS Export Rating Curves= 0
DSS Export Rating Curve Sorted= 0
DSS Export Volume Flow Curves= 0
DXF OffsetX= 0
DXF OffsetY= 0
DXF ScaleX= 0
DXF ScaleY= 0

--- ELKRIVT1.p01 (plan) ---

Plan Title=Floodplain
Program Version=6.20
Short Identifier=Floodplain
Geom File=g01
Flow File=f01
Subcritical Flow
K Sum by GR= 0
Std Step Tol= 0.01
Critical Tol= 0.01
Num of Std Step Trials= 20
Max Error Tol= 0.3
Flow Tol Ratio= 0.001
Split Flow NTrial= 30
Split Flow Tol= 0.02
Split Flow Ratio= 0.02
Log Output Level= 0
Friction Slope Method= 1
Unsteady Friction Slope Method= 2
Unsteady Bridges Friction Slope Method= 1
Parabolic Critical Depth
Global Vel Dist= 0 , 0 , 0
Global Log Level= 0
CheckData=True
Encroach Param=-1 ,0,0, 0
Mapping Interval=1HOUR
Computation Time Step Use Courant=        0
Computation Time Step Use Time Series=    0
Computation Time Step Count To Double=0
Computation Time Step Max Doubling=0
Computation Time Step Max Halving=0
Computation Time Step Residence Courant=0
Run HTab= 0
Run UNet= 0
Run Sediment= 0
Run PostProcess= 0
Run WQNet= 0
Run RASMapper=-1
UNET Theta= 0
UNET Theta Warmup= 0
UNET ZTol= 0
UNET ZSATol= 0
UNET MxIter= 0
UNET Max Iter WO Improvement= 0
UNET MaxInSteps= 0
UNET DtIC= 0
UNET DtMin= 0
UNET MaxCRTS= 0
UNET WFStab= 0
UNET SFStab= 0
UNET WFX= 1
UNET SFX= 1
UNET Gravity=32.174
UNET 1D Methodology=Finite Difference
UNET DSS MLevel= 1
UNET Pardiso=0
UNET DZMax Abort= 0
UNET Use Existing IB Tables= 0
UNET Froude Reduction=False
UNET Froude Limit= 0
UNET Froude Power= 0
UNET D1 Cores= 0
UNET WindReference=Eulerian
UNET WindDragFormulation=Hsu (1988)
UNET D2 Coriolis=0
UNET D2 Cores= 0
UNET D2 Theta= 1
UNET D2 Theta Warmup= 1
UNET D2 Z Tol= 0.01
UNET D2 Volume Tol= 0.01
UNET D2 Max Iterations= 20
UNET D2 Equation= 0
UNET D2 RampUpFraction=0.1
UNET D2 TimeSlices= 1
UNET D2 Turbulence Formulation=Non-Conservative (original)
UNET D2 Eddy Viscosity=0.3
UNET D2 Transverse Eddy Viscosity=0.1
UNET D2 Smagorinsky Mixing=0
UNET D2 BCVolumeCheck=0
UNET D2 Cores=0
UNET D2 SolverType=PARDISO (Direct)
UNET D2 Minimum Iterations= 2147483647
UNET D2 Maximum Iterations= 2147483647
UNET D2 Restart Number= 10
UNET D2 Relaxation Coeff=1.3
UNET D2 SOR Precondition Iterations= 10
UNET D2 ILUT Maximum Fill= 8
UNET D2 ILUT Tolerance=1E-08
UNET D1D2 MaxIter= 0
UNET D1D2 ZTol=0.01
UNET D1D2 QTol=0.1
UNET D1D2 MinQTol=1
Write IC File= 0
Write IC File at Fixed DateTime=0
Write IC File at Sim End=0
Echo Input=False
Echo Parameters=False
Echo Output=False
Write Detailed= 0
HDF Write Warmup=0
HDF Write Time Slices=0
HDF Flush=0
HDF Compression= 1
HDF Chunk Size= 1
HDF Spatial Parts= 1
HDF Use Max Rows=0
HDF Fixed Rows= 1
Calibration Method= 0
Calibration Iterations= 20
Calibration Max Change=0.05
Calibration Tolerance=0.2
Calibration Maximum=1.5
Calibration Minimum=0.5
Calibration Optimization Method= 1
WQ AD Non Conservative
WQ ULTIMATE=-1
WQ Max Comp Step=1HOUR
WQ Output Interval=15MIN
WQ Output Selected Increments= 0
WQ Output face flow=0
WQ Output face velocity=0
WQ Output face area=0
WQ Output face dispersion=0
WQ Output cell volume=0
WQ Output cell surface area=0
WQ Output cell continuity=0
WQ Output cumulative cell continuity=0
WQ Output face conc=0
WQ Output face dconc_dx=0
WQ Output face courant=0
WQ Output face peclet=0
WQ Output face adv mass=0
WQ Output face disp mass=0
WQ Output cell mass=0
WQ Output cell source sink temp=0
WQ Output nsm pathways=0
WQ Output nsm derived pathways=0
WQ Create Restart=0
WQ Fixed Restart=0
WQ System Summary=0
WQ Write To DSS=0
Sorting and Armoring Iterations= 10
XS Update Threshold= 0.02
Bed Roughness Predictor= 0
Hydraulics Update Threshold= 0.02
Energy Slope Method= 1
Volume Change Method= 1
Sediment Retention Method= 0
Sediment TS Multiplier= 1
Warm Up Method= 0
XS Weighting Method= 0
Number of US Weighted Cross Sections= 1
Number of DS Weighted Cross Sections= 1
Upstream XS Weight=0
Main XS Weight=1
Downstream XS Weight=0
Number of DS XS's Weighted with US Boundary= 1
Upstream Boundary Weight= 1
Weight of XSs Associated with US Boundary= 0
Number of US XS's Weighted with DS Boundary= 1
Downstream Boundary Weight= 0.5
Weight of XSs Associated with DS Boundary= 0.5
Percentile Method= 0
Sediment Output Level= 3
Mass or Volume Output= 0
Output Increment Type= 1
Profile and TS Output Increment= 1
Transport Output Increment 1
XS Output Flag= 0
XS Output Increment= 10
Read HDF5 Sediment Hotstart= 0
Sediment Hotstart Type= 0
Write Gradation File= 0
Read Gradation Hotstart= 0
Write HDF5 File= 1
Write Binary Output= 1
Write DSS Sediment File= 0
DSS Sediment Output Type= 1
SV Curve= 0
Specific Gage Flag= 0
Subcell Erosion Methods= 0
Subcell Deposition Methods= 0
Advection Scheme= 1
Matrix Solver= 0
Implicit Weighting Factor= 1
Maximum Outer Loop Convergence Iterations= 5
Convergence Maximum Absolute= 0.001
Convergence RMSE= 0.0001
Grain Fractions Max Abs Error= 0.001
Max Subgrid Regions= 1
Max Subgrid Length Scale= 3.402823E+38
Initial Layer Thickness= 3.402823E+38
Min Layer Thickness= 3.402823E+38
Max Layer Thickness= 3.402823E+38
Number of Layers= 5

--- ELKRIVT1.f01 (steady flow) ---

Flow Title=Flow
Program Version=6.20
Number of Profiles= 1
Profile Names=P100yr
River Rch & RM=ELKRIVT1,Main            ,1107
     285
Boundary for River Rch & Prof#=ELKRIVT1,Main            , 1
Up Type= 0
Dn Type= 3
Dn Slope=0.04544
DSS Import GetInterval= 0
DSS Import GetPeak= 0
DSS Import FillOption= 0

--- ELKRIVT1.g01 (geometry) ---

Geom Title=Geometry
Program Version=6.20

River Reach=ELKRIVT1        ,Main
Reach XY= 30
2218040.82180846543277.343180686 2218075.8414776543272.618914545
2218096.62579958543260.2954670192218140.40162808543246.990796253
2218173.70619735543230.843126327  2218191.872326543227.058516189
2218296.56400003543244.6770000012218372.08400001543250.927000001
     2218427.293543247.2810000182218440.42900002543241.601000011
2218466.87599999543217.5939999972218483.54300003543195.197999999
     2218499.168 543162.907000022218514.35800003543120.833000004
     2218543.766543067.9910000122218592.30600001543045.096000001
2218624.10200001543020.4710000162218645.54800001543015.510000005
2218667.96200001543018.5550000222218682.81299999543024.720000014
2218698.95103467543037.555757597      2218719.48543064.468999997
2218761.47153006543130.0469624252218787.56541465543142.016415462
2218827.25500865543173.7949079872218856.88811778543207.986956924
2218857.15629067543226.2227163462218864.64199891543252.366369211
2218858.90725061 543263.085778442218845.24500002543275.677000001

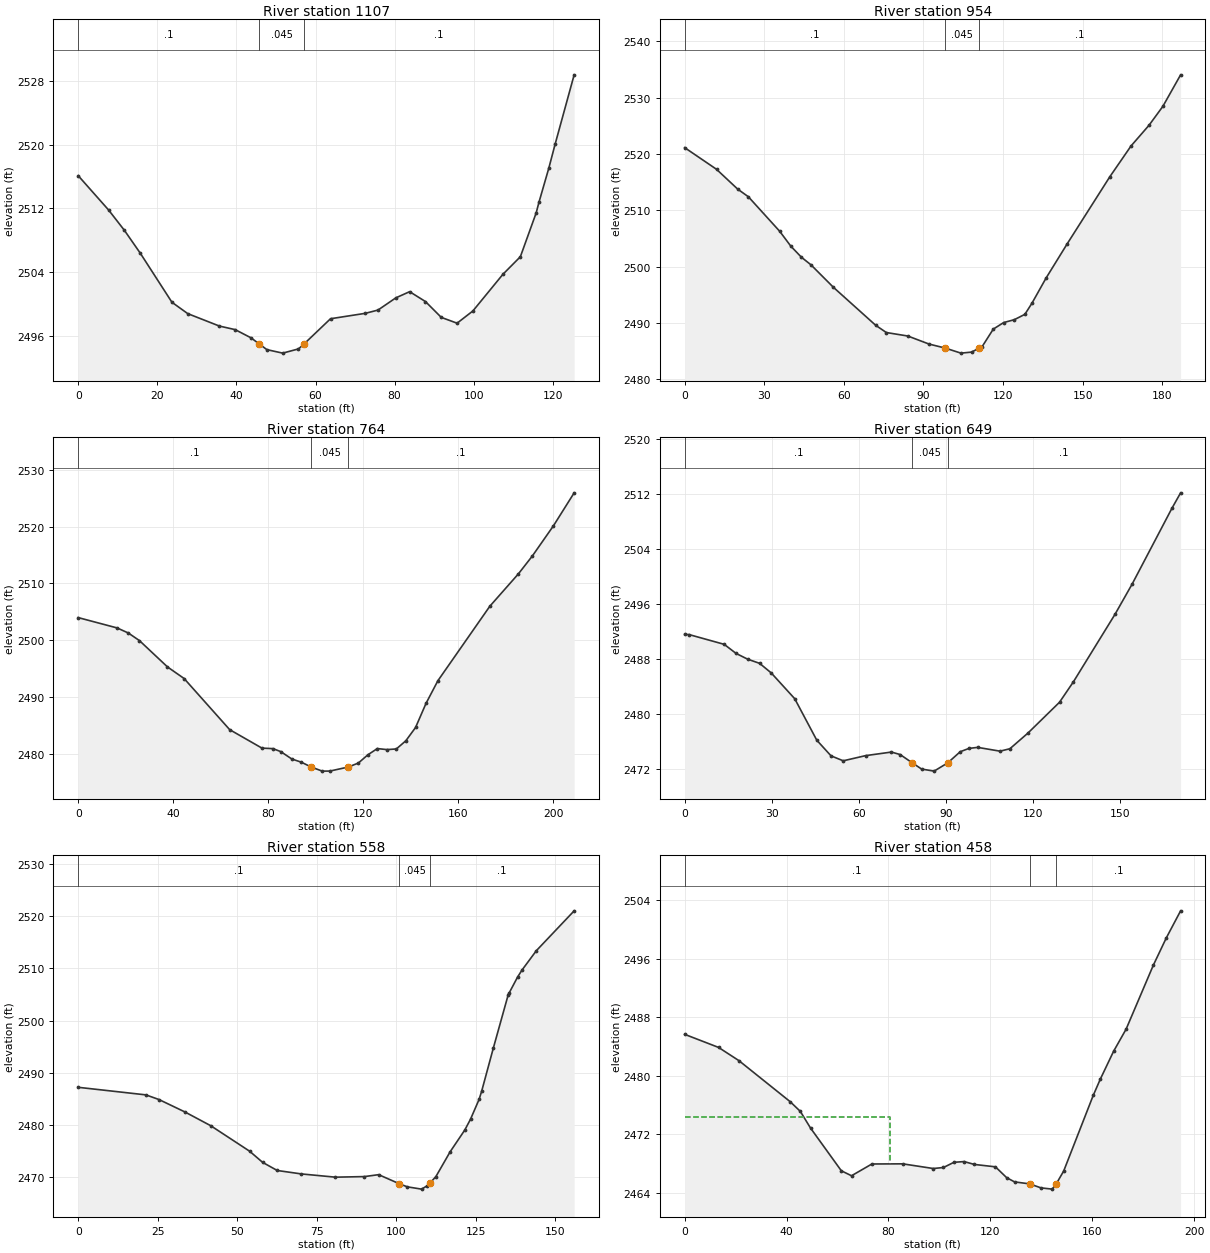
Type RM Length L Ch R = 1 ,1107    ,152.9,153.3,152.9
XS GIS Cut Line= 2
2218043.42368704543328.8951564182218039.19356851 543203.52982546
#Sta/Elev= 30
       0 2516.12     7.7  2511.8    11.7 2509.24    15.7 2506.38    23.7 2500.22
    27.7 2498.79    35.7 2497.23    39.7 2496.78    43.7 2495.75   45.752494.991
    47.7 2494.27    51.7 2493.83    55.7 2494.36    57.1 2494.98    63.8 2498.15
    72.6 2498.83    75.8 2499.24    80.3 2500.77    83.8 2501.55    87.8 2500.31
    91.8 2498.32    95.8 2497.59    99.8 2499.13   107.4 2503.74   111.8 2505.94
   115.8 2511.45   116.5 2512.78     119 2517.08   120.6  2520.1   125.4 2528.79
#Mann= 3 ,-1,0
       0      .1       0   45.75    .045       0    57.1      .1       0
Bank Sta=45.75,57.1
XS Rating Curve= 0 ,0
Exp/Cntr(USF)=0,0
Exp/Cntr=0.3,0.1

Type RM Length L Ch R = 1 ,954     ,189.4,190.1,190.1
XS GIS Cut Line= 4
2218188.41156145543333.2019356092218187.41985104543260.807075858
 2218182.6765309543199.6182461012218181.10236481543146.563980068
#Sta/Elev= 30
       0 2521.13      12 2517.28      20 2513.75      24  2512.4    35.8 2506.27
      40 2503.62      44 2501.65    47.6  2500.3      56 2496.33      72 2489.55
      76 2488.27    84.1 2487.65    92.1 2486.22   98.212485.505   104.1 2484.61
   108.1 2484.79  111.022485.505   112.1 2485.77   116.3 2488.88   120.2 2490.04
   124.2 2490.55   128.2  2491.5   130.9  2493.5   136.2 2497.96   144.2 2504.07
   160.2 2515.94   168.2 2521.42     175 2525.11   180.2 2528.46   186.9 2534.07
#Mann= 3 ,-1,0
       0      .1       0   98.21    .045       0  111.02      .1       0
Bank Sta=98.21,111.02
XS Rating Curve= 0 ,0
Exp/Cntr(USF)=0,0
Exp/Cntr=0.3,0.1

Type RM Length L Ch R = 1 ,764     ,121.7,114.7,107.3
XS GIS Cut Line= 4
2218330.39871197543343.1543502382218372.89619049543274.033628396
2218373.11948303543213.7128262242218342.92261564543153.436848101
#Sta/Elev= 30
       0 2503.99    16.4 2502.17    21.1 2501.28    25.8 2499.94    37.6 2495.31
    44.6 2493.27    63.8 2484.27    77.4 2481.02      82 2480.93    85.3 2480.41
      90  2479.1      94 2478.54   98.16 2477.69   102.8 2476.97     106 2476.98
  113.73 2477.69     118 2478.39     122 2479.84     126 2480.94     130 2480.76
     134 2480.87     138 2482.31   142.1 2484.65   146.5 2488.89   151.5 2492.88
   173.4    2506   185.4 2511.68   191.3 2514.84   200.2 2520.16   208.9 2525.95
#Mann= 3 ,-1,0
       0      .1       0   98.16    .045       0  113.73      .1       0
Bank Sta=98.16,113.73
XS Rating Curve= 0 ,0
Exp/Cntr(USF)=0,0
Exp/Cntr=0.3,0.1

Type RM Length L Ch R = 1 ,649     ,91.3,91.1,91.1
XS GIS Cut Line= 4
2218518.12035166543270.6293774292218511.81065673543229.661825592
2218443.68027099543194.3297799362218415.10791772543150.205286383
#Sta/Elev= 30
       0 2491.57     1.5 2491.56    13.6 2490.14    17.7 2488.82    21.7 2487.98
    25.8 2487.38    29.8 2485.99    37.9 2482.24    45.5 2476.21    50.4 2473.94
    54.6 2473.22    62.3 2473.97    71.2 2474.49    74.2 2474.13   78.412472.915
    81.6 2472.02    85.9 2471.72    90.6 2472.92    94.9 2474.54    97.9 2475.02
   100.9 2475.17   108.6 2474.62     112 2474.97   118.2 2477.24   129.1 2481.73
   133.9 2484.71   148.2  2494.5   154.1 2498.89   167.8  2509.9   170.8 2512.15
#Mann= 3 ,0,0
       0      .1       0   78.41    .045       0    90.6      .1       0
Bank Sta=78.41,90.6
XS Rating Curve= 0 ,0
Exp/Cntr(USF)=0,0
Exp/Cntr=0.3,0.1

Type RM Length L Ch R = 1 ,558     ,95.8,100.1,102.2
XS GIS Cut Line= 3
 2218552.6238907543214.1356168352218538.60344811543141.787708282
2218465.68277633543103.718647972
#Sta/Elev= 30
       0 2487.24    21.3 2485.79    25.4  2484.9    33.6 2482.51    41.7 2479.88
    53.9 2475.01      58 2472.87    62.6 2471.31    70.2 2470.65    80.9 2470.03
      90 2470.14    94.5 2470.51   100.9  2468.8   103.5 2468.18     108 2467.74
   109.6 2468.32  110.63  2468.9   112.5 2470.13     117  2474.9   121.6 2479.06
   123.4 2481.13   126.1 2484.93   126.9 2486.48   130.6  2494.8   135.2 2504.84
   135.5 2505.25   138.2 2508.35   139.6  2509.7   144.1  2513.4     156 2521.04
#Mann= 3 ,0,0
       0      .1       0   100.9    .045       0  110.63      .1       0
Bank Sta=100.9,110.63
XS Rating Curve= 0 ,0
Exp/Cntr(USF)=0,0
Exp/Cntr=0.3,0.1

Type RM Length L Ch R = 1 ,458     ,118.3,125.4,129.2
XS GIS Cut Line= 4
2218572.87154247543194.4217979582218583.39310078 543075.59618013
2218566.91858262543042.647143815 2218542.3513187543012.877400478
#Sta/Elev= 30
       0 2485.68    13.3 2483.89    21.3 2482.08    41.4 2476.47    45.4 2475.14
    49.4 2472.86    61.5 2467.01    65.5 2466.33    73.5 2467.94    85.6 2467.96
    97.6 2467.32   101.6 2467.46   105.7 2468.17   109.7 2468.27   113.7 2467.88
     122 2467.55   126.4 2466.07   129.5 2465.49   135.4 2465.22   139.9 2464.67
   144.3  2464.5  145.932465.254   148.8 2466.98   160.4 2477.33   163.2 2479.57
   168.4 2483.37   173.3 2486.39     184 2495.15   189.1 2498.89   194.7 2502.58
#Mann= 3 ,0,0
       0      .1       0   135.4    .045       0  145.93      .1       0
#XS Ineff= 2 , 0
           80.55 2474.42
Permanent Ineff=
       F       F
Bank Sta=135.4,145.93
XS Rating Curve= 0 ,0
Exp/Cntr(USF)=0,0
Exp/Cntr=0.3,0.1

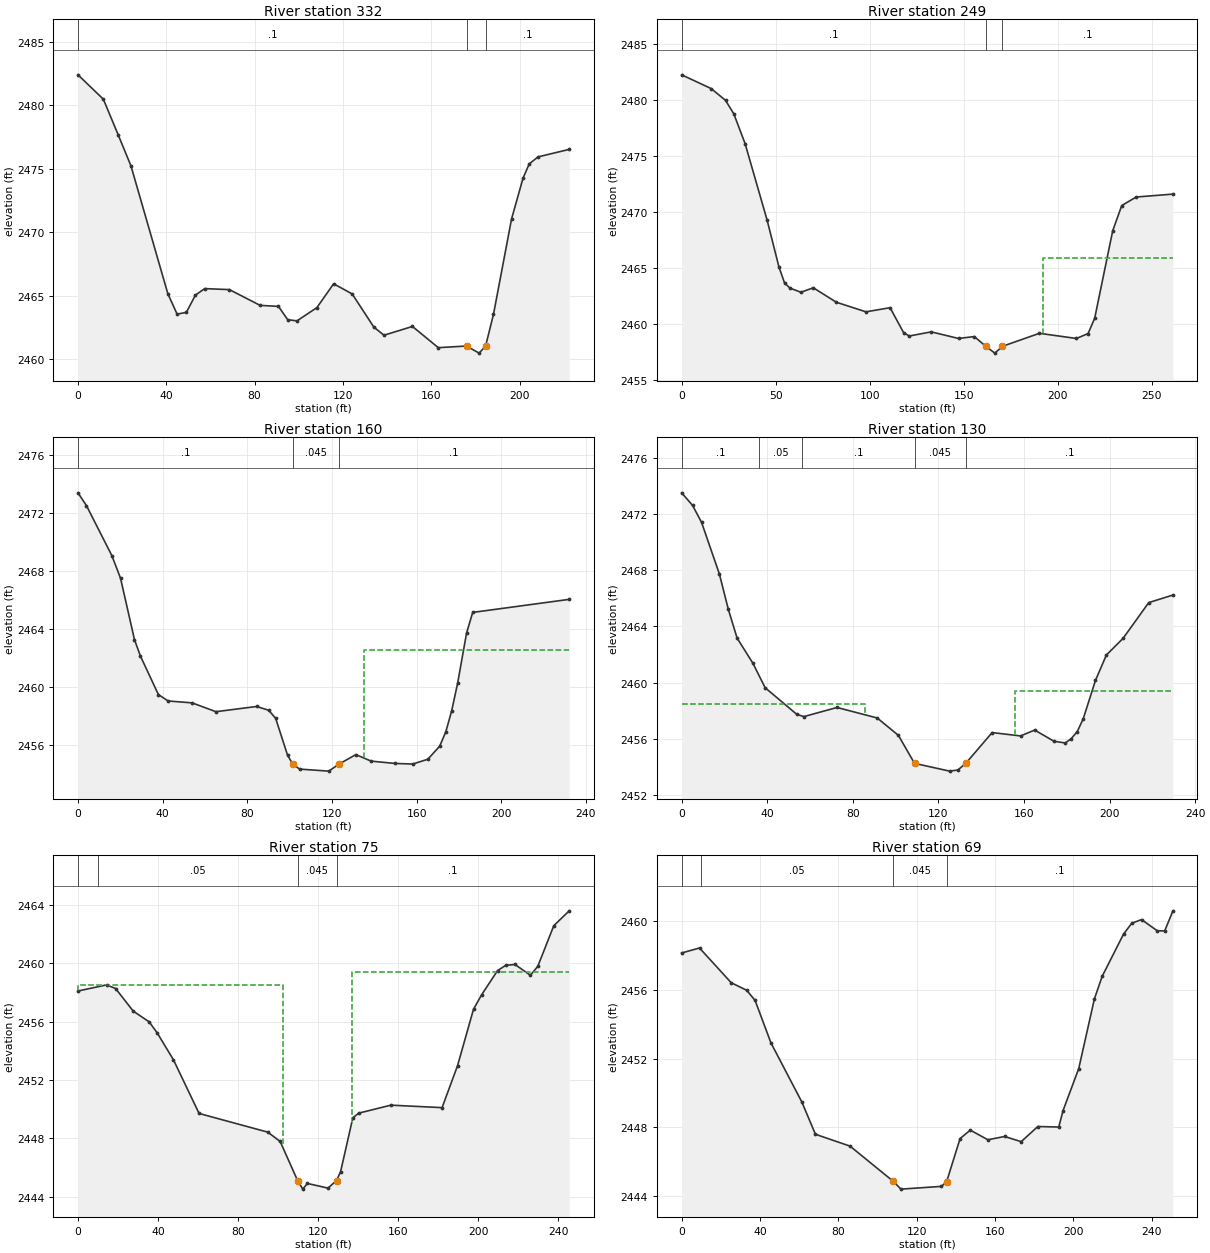
Type RM Length L Ch R = 1 ,332     ,81.7,82.8,83.6
XS GIS Cut Line= 4
2218612.59842209543188.216281821 2218649.8666884543062.964170296
2218689.82441723543020.7011878792218692.79126195542987.157664716
#Sta/Elev= 30
       0 2482.38    11.5 2480.46    18.2 2477.66      24 2475.21    40.7 2465.15
    44.9 2463.54    49.1 2463.68    53.2 2465.04    57.4 2465.55    68.6 2465.47
    82.5 2464.23    90.8 2464.15      95  2463.1    99.2 2463.01   108.2 2464.05
   115.8 2465.93   124.2 2465.13     134 2462.52   138.6 2461.88   151.5 2462.57
   163.2  2460.9     176 2461.03   181.7 2460.47  184.642461.036   188.2 2463.52
   196.4 2471.04   201.6 2474.25   204.4 2475.37   208.4 2475.92   222.5 2476.51
#Mann= 3 ,-1,0
       0      .1       0     176    .045       0  184.64      .1       0
Bank Sta=176,184.64
XS Rating Curve= 0 ,0
Exp/Cntr(USF)=0,0
Exp/Cntr=0.3,0.1

Type RM Length L Ch R = 1 ,249     ,90.2,89.2,88.1
XS GIS Cut Line= 4
2218620.45444528543202.2798698352218643.96500325543152.251253248
2218793.26722558 543051.552504282218794.72362484543025.787362967
#Sta/Elev= 30
       0 2482.26    15.7 2481.03    23.3 2479.98    27.7 2478.78    33.7 2476.12
    45.4 2469.29    51.7  2465.1    54.7 2463.66    57.6  2463.2    63.4 2462.83
      70 2463.23    82.2 2461.94      98 2461.08   110.8 2461.45     118 2459.22
     121 2458.92   132.7 2459.29   147.2  2458.7   155.6 2458.87   161.7    2458
   166.5 2457.39  170.58    2458   190.2 2459.16   209.9  2458.7   216.1 2459.14
   219.6  2460.5   229.2 2468.33     234 2470.58   241.7 2471.34   261.2  2471.6
#Mann= 3 ,-1,0
       0      .1       0   161.7    .045       0  170.58      .1       0
#XS Ineff= 2 , 0
                          192.19          2465.9
Permanent Ineff=
       F       F
Bank Sta=161.7,170.58
XS Rating Curve= 0 ,0
Exp/Cntr(USF)=0,0
Exp/Cntr=0.3,0.1

Type RM Length L Ch R = 1 ,160     ,28.7,30.7,31.3
BEGIN DESCRIPTION:
structure xs 4
END DESCRIPTION:
XS GIS Cut Line= 4
2218713.49965312543236.197980833 2218727.7688501543220.189042999
2218844.23720461543103.0700272892218841.75623346543057.635006467
#Sta/Elev= 30
       0 2473.41       4 2472.53      16 2469.08    20.1 2467.52    26.7 2463.28
    29.5 2462.15      38 2459.49    42.6 2459.05    53.9 2458.92    65.2 2458.31
    84.4 2458.67    90.1 2458.41    93.4 2457.85      99 2455.32   101.4 2454.71
   104.7 2454.35   118.5 2454.21  123.452454.706   131.3 2455.35   138.5  2454.9
   149.8 2454.74   158.2  2454.7   165.3 2455.03   170.9 2455.93   173.8 2456.92
   176.6 2458.39   179.4 2460.29   183.6 2463.73   186.5 2465.16   232.1 2466.06
#Mann= 3 ,-1,0
       0      .1       0   101.4    .045       0  123.45      .1       0
#XS Ineff= 2 , 0
                          135.07         2462.58
Permanent Ineff=
       F       F
Bank Sta=101.4,123.45
XS Rating Curve= 0 ,0
Exp/Cntr(USF)=0,0
Exp/Cntr=0.3,0.1

Type RM Length L Ch R = 1 ,130     ,55.1,54.9,54.7
BEGIN DESCRIPTION:
structure xs 3
END DESCRIPTION:
XS GIS Cut Line= 4
2218715.30177975543238.6541555732218750.10916422543228.328030861
2218875.08072299543124.9453540442218875.58502195543093.812960592
#Sta/Elev= 30
       0 2473.53     5.1 2472.63     9.3 2471.42    17.6 2467.75    21.8 2465.22
    25.9 2463.17    33.3 2461.37      39 2459.63    53.8 2457.73    57.1 2457.57
    72.6 2458.22    91.4 2457.47   101.3 2456.23  108.822454.236   125.2 2453.68
   129.1 2453.76   132.82454.237   145.1 2456.43   158.4 2456.19     165 2456.61
     174 2455.81   179.3 2455.69   182.1    2456   184.9  2456.5   187.7 2457.42
   193.4 2460.15   198.5 2461.96   206.3 2463.15   218.3  2465.7   229.6 2466.24
#Mann= 5 ,-1,0
       0      .1       0   36.31     .05       0   56.31      .1       0
  108.82    .045       0   132.8      .1       0
#XS Ineff= 2 , 0
           85.82  2458.5   155.8          2459.4
Permanent Ineff=
       F       F
Bank Sta=108.82,132.8
XS Rating Curve= 0 ,0
Exp/Cntr(USF)=0,0
Exp/Cntr=0.3,0.1

Type RM Length L Ch R = 1 ,75      ,7.5,6,4.9
BEGIN DESCRIPTION:
structure xs 2
END DESCRIPTION:
XS GIS Cut Line= 4
2218748.69271718543255.6983340592218808.96012909543250.161719461
2218902.56052917543172.9155851772218899.60694775543109.509641515
#Sta/Elev= 30
       0  2458.1    14.3 2458.52    18.8 2458.27    27.6 2456.72    35.6 2455.98
    39.6 2455.22    47.7 2453.38    60.5  2449.7    94.8 2448.42     101 2447.78
   109.72445.101   112.3 2444.51   114.6  2444.9   124.9 2444.58  129.172445.101
   131.2 2445.71   137.3  2449.4   140.2 2449.72   156.3 2450.27   181.9  2450.1
   189.6 2452.97   197.6 2456.85   201.6 2457.83   209.6  2459.5   213.7 2459.86
   218.3 2459.92     226 2459.18   229.7 2459.79   237.7 2462.58   245.4  2463.6
#Mann= 4 ,-1,0
       0      .1       0      10     .05       0   109.7    .045       0
  129.17      .1       0
#XS Ineff= 2 , 0
           102.2  2458.5  136.67          2459.4
Permanent Ineff=
       F       F
Bank Sta=109.7,129.17
XS Rating Curve= 0 ,0
Exp/Cntr(USF)=0,0
Exp/Cntr=0.3,0.1

Type RM Length L Ch R = 1 ,69      ,,,
BEGIN DESCRIPTION:
structure xs 1
END DESCRIPTION:
XS GIS Cut Line= 5
2218747.19204054543262.8789873212218814.26609665543251.725371193
2218880.01346653543197.4123265072218909.48919247543171.403813854
2218912.24763788543113.124765565
#Sta/Elev= 30
       0 2458.14     9.1 2458.43    25.3 2456.41    33.2 2455.97    37.5 2455.38
    45.6 2452.91    61.4 2449.47    68.3  2447.6      86 2446.91   108.1 2444.86
     112 2444.41   132.7 2444.57  135.322444.842   142.2 2447.35   147.4 2447.84
   156.4 2447.28   164.9 2447.47   173.4 2447.17   181.9 2448.05   192.6 2448.02
   194.8 2448.98   202.8 2451.42   210.8 2455.47   214.8 2456.79   225.7 2459.24
   229.9 2459.87   234.9 2460.08   242.9 2459.43   246.7 2459.42   250.9 2460.59
#Mann= 4 ,-1,0
       0      .1       0      10     .05       0   108.1    .045       0
  135.32      .1       0
Bank Sta=108.1,135.32
XS Rating Curve= 0 ,0
Exp/Cntr(USF)=0,0
Exp/Cntr=0.3,0.1
LCMann Table=0

Chan Stop Cuts=-1
Use User Specified Reach Order=0
Composite Channel Slope=5